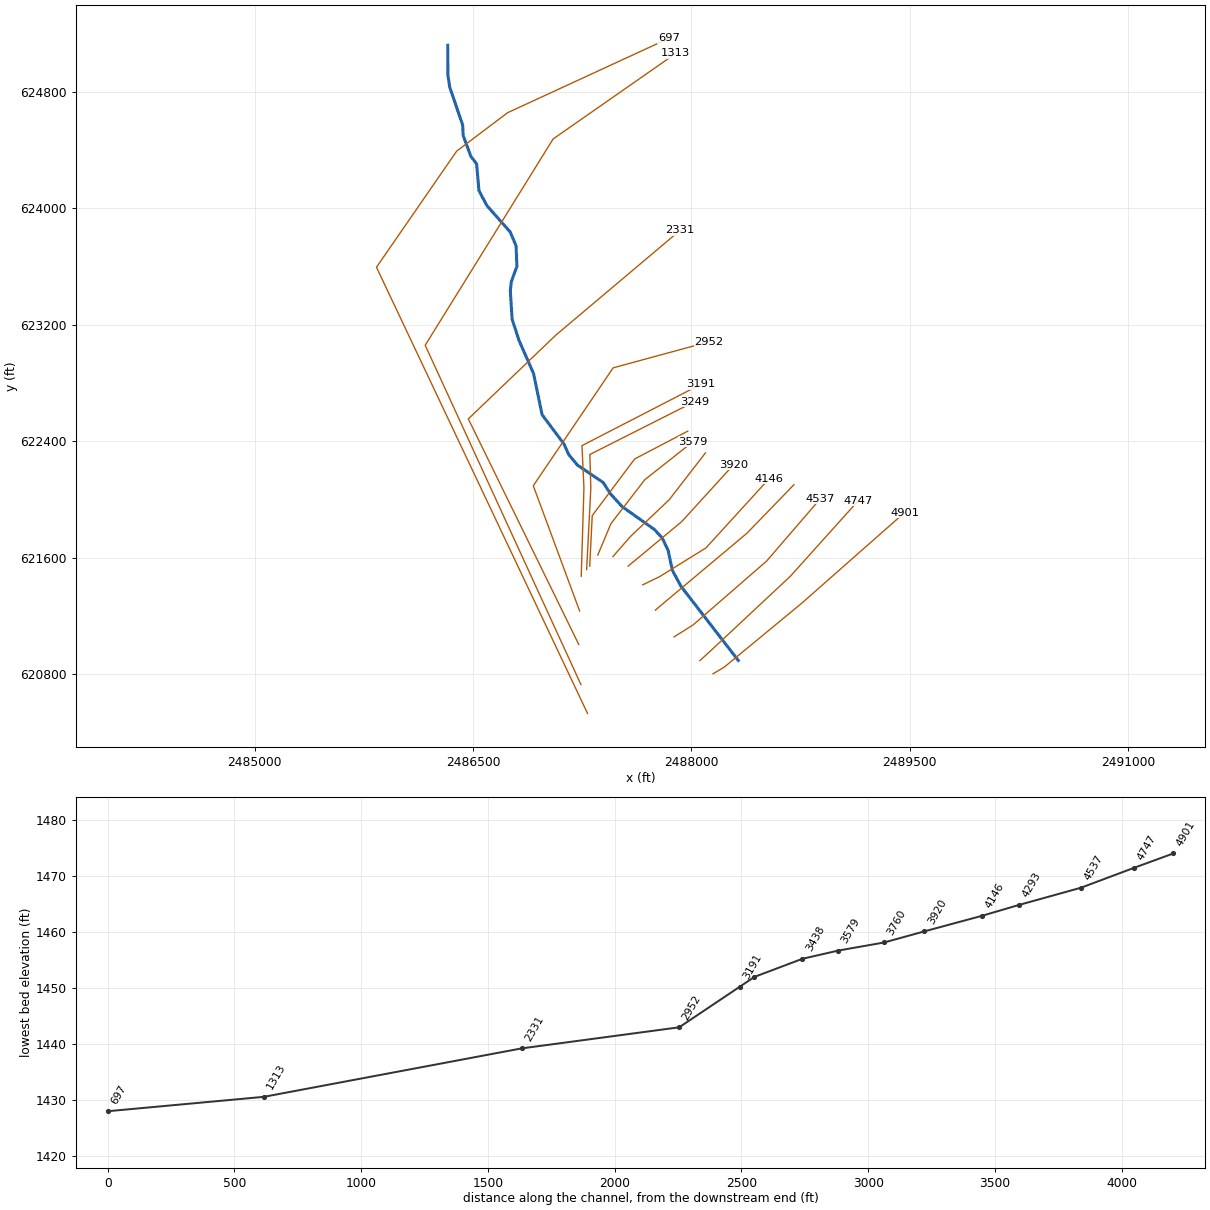
--- FISHERRN.prj (project) ---

Proj Title=FISHERRN
Current Plan=p01
Default Exp/Contr=0,0
English Units
Geom File=g01
Flow File=f01
Plan File=p01
BEGIN DESCRIPTION:
Stream Name:Fisher Run
Flood Zone: Zone A
Pendleton County, WV
WVDHSEM Flood Warning & Analysis Mapping
HEC-RAS Version: 5.0.7
Hydrology Method:
Regression was used
Model Notes:
Model ties in with South Fork South Branch South Potomac River
END DESCRIPTION:
DSS Export Rating Curves= 0
DSS Export Rating Curve Sorted= 0
DSS Export Volume Flow Curves= 0
DXF OffsetX= 0
DXF OffsetY= 0
DXF ScaleX= 0
DXF ScaleY= 0

--- FISHERRN.p01 (plan) ---

Plan Title=Floodplain
Program Version=5.07
Short Identifier=Floodplain
Geom File=g01
Flow File=f01
Subcritical Flow
K Sum by GR= 0
Std Step Tol= 0.01
Critical Tol= 0.01
Num of Std Step Trials= 20
Max Error Tol= 0.3
Flow Tol Ratio= 0.001
Split Flow NTrial= 30
Split Flow Tol= 0.02
Split Flow Ratio= 0.02
Log Output Level= 0
Friction Slope Method= 1
Unsteady Friction Slope Method= 2
Unsteady Bridges Friction Slope Method= 1
Parabolic Critical Depth
Global Vel Dist= 0 , 0 , 0
Global Log Level= 0
CheckData=True
Encroach Param=-1 ,0,0, 0
Mapping Interval=1HOUR
Computation Time Step Use Courant=        0
Computation Time Step Use Time Series=    0
Computation Time Step Count To Double=0
Computation Time Step Max Doubling=0
Computation Time Step Max Halving=0
Computation Time Step Residence Courant=0
Run HTab= 0
Run UNet= 0
Run Sediment= 0
Run PostProcess= 0
Run WQNet= 0
Run RASMapper= 0
UNET Theta= 0
UNET Theta Warmup= 0
UNET ZTol= 0
UNET ZSATol= 0
UNET MxIter= 0
UNET Max Iter WO Improvement= 0
UNET MaxInSteps= 0
UNET DtIC= 0
UNET DtMin= 0
UNET MaxCRTS= 0
UNET WFStab= 0
UNET SFStab= 0
UNET WFX= 1
UNET SFX= 1
UNET 1D Methodology=Finite Difference
UNET DSS MLevel= 1
UNET Pardiso=0
UNET DZMax Abort= 0
UNET Use Existing IB Tables= 0
UNET Froude Reduction=False
UNET Froude Limit= 0
UNET Froude Power= 0
UNET D1 Cores= 0
UNET D2 Coriolis=0
UNET D2 Cores= 0
UNET D2 Theta= 1
UNET D2 Theta Warmup= 1
UNET D2 Z Tol= 0.01
UNET D2 Volume Tol= 0.01
UNET D2 Max Iterations= 20
UNET D2 Equation= 0
UNET D2 RampUpFraction=0.1
UNET D2 TimeSlices= 1
UNET D2 BCVolumeCheck=0
UNET D1D2 MaxIter= 0
UNET D1D2 ZTol=0.01
UNET D1D2 QTol=0.1
UNET D1D2 MinQTol=1
Write IC File= 0
Write IC File at Fixed DateTime=0
Write IC File at Sim End=0
Echo Input=False
Echo Parameters=False
Echo Output=False
Write Detailed= 0
HDF Write Warmup=0
HDF Write Time Slices=0
HDF Flush=0
HDF Face Node Velocities=0
HDF Compression= 1
HDF Chunk Size= 1
HDF Spatial Parts= 1
HDF Use Max Rows=0
HDF Fixed Rows= 1
Calibration Method= 0
Calibration Iterations= 20
Calibration Max Change=0.05
Calibration Tolerance=0.2
Calibration Maximum=1.5
Calibration Minimum=0.5
Calibration Optimization Method= 1
WQ AD Non Conservative
WQ ULTIMATE=-1
WQ Max Comp Step=1HOUR
WQ Output Interval=15MIN
WQ Output Selected Increments= 0
WQ Output face flow=0
WQ Output face velocity=0
WQ Output face area=0
WQ Output face dispersion=0
WQ Output cell volume=0
WQ Output cell surface area=0
WQ Output cell continuity=0
WQ Output cumulative cell continuity=0
WQ Output face conc=0
WQ Output face dconc_dx=0
WQ Output face courant=0
WQ Output face peclet=0
WQ Output face adv mass=0
WQ Output face disp mass=0
WQ Output cell mass=0
WQ Output cell source sink temp=0
WQ Output nsm pathways=0
WQ Output nsm derived pathways=0
WQ Output MaxMinRange=-1
WQ Daily Max Min Mean=-1
WQ Daily Range=0
WQ Daily Time=0
WQ Create Restart=0
WQ Fixed Restart=0
WQ System Summary=0
WQ Write To DSS=0
WQ Use Fixed Temperature=0
Sorting and Armoring Iterations= 10
XS Update Threshold= 0.02
Bed Roughness Predictor= 0
Hydraulics Update Threshold= 0.02
Energy Slope Method= 1
Volume Change Method= 1
Sediment Retention Method= 0
XS Weighting Method= 0
Number of US Weighted Cross Sections= 1
Number of DS Weighted Cross Sections= 1
Upstream XS Weight=0
Main XS Weight=1
Downstream XS Weight=0
Number of DS XS's Weighted with US Boundary= 1
Upstream Boundary Weight= 1
Weight of XSs Associated with US Boundary= 0
Number of US XS's Weighted with DS Boundary= 1
Downstream Boundary Weight= 0.5
Weight of XSs Associated with DS Boundary= 0.5
Percentile Method= 0
Sediment Output Level= 3
Mass or Volume Output= 0
Output Increment Type= 1
Profile and TS Output Increment= 1
XS Output Flag= 0
XS Output Increment= 10
Write Gradation File= 0
Read Gradation Hotstart= 0
Write HDF5 File= 1
Write Binary Output= 1
Write DSS Sediment File= 0
SV Curve= 0
Specific Gage Flag= 0

--- FISHERRN.f01 (steady flow) ---

Flow Title=Flows
Program Version=5.07
Number of Profiles= 6
Profile Names=P100yr,P10yr,P25yr,P50yr,P500yr,P101yr
River Rch & RM=FISHERRN,Main            ,4901
     802     373     529     662    1180     976
Boundary for River Rch & Prof#=FISHERRN,Main            , 1
Up Type= 0
Dn Type= 3
Dn Slope=0.00728
Boundary for River Rch & Prof#=FISHERRN,Main            , 2
Up Type= 0
Dn Type= 3
Dn Slope=0.00728
Boundary for River Rch & Prof#=FISHERRN,Main            , 3
Up Type= 0
Dn Type= 3
Dn Slope=0.00728
Boundary for River Rch & Prof#=FISHERRN,Main            , 4
Up Type= 0
Dn Type= 3
Dn Slope=0.00728
Boundary for River Rch & Prof#=FISHERRN,Main            , 5
Up Type= 0
Dn Type= 3
Dn Slope=0.00728
Boundary for River Rch & Prof#=FISHERRN,Main            , 6
Up Type= 0
Dn Type= 3
Dn Slope=0.00728
DSS Import GetInterval= 0
DSS Import GetPeak= 0
DSS Import FillOption= 0

--- FISHERRN.g01 (geometry) ---

Geom Title=Geometry
Program Version=5.07

River Reach=FISHERRN        ,Main
Reach XY= 30
     2488322.904      620894.543     2487928.165      621405.305
     2487869.716      621514.177     2487840.212      621652.223
     2487800.161      621735.547     2487747.123      621793.981
     2487524.688      621951.728     2487444.215      622039.843
     2487394.081      622117.662     2487218.652      622236.075
     2487157.574      622308.906     2487125.489      622381.309
      2486974.75      622583.089     2486916.339      622865.436
     2486816.447      623092.983     2486769.058       623237.49
     2486756.409      623435.645     2486763.652      623497.285
      2486801.67      623601.609     2486795.903      623744.058
      2486755.52      623838.586     2486596.068      624019.042
      2486541.02      624122.591     2486525.043      624306.058
     2486485.259      624357.977     2486432.385      624502.527
     2486429.493      624571.335     2486340.198      624834.367
     2486328.028      624912.855     2486326.342      625120.872

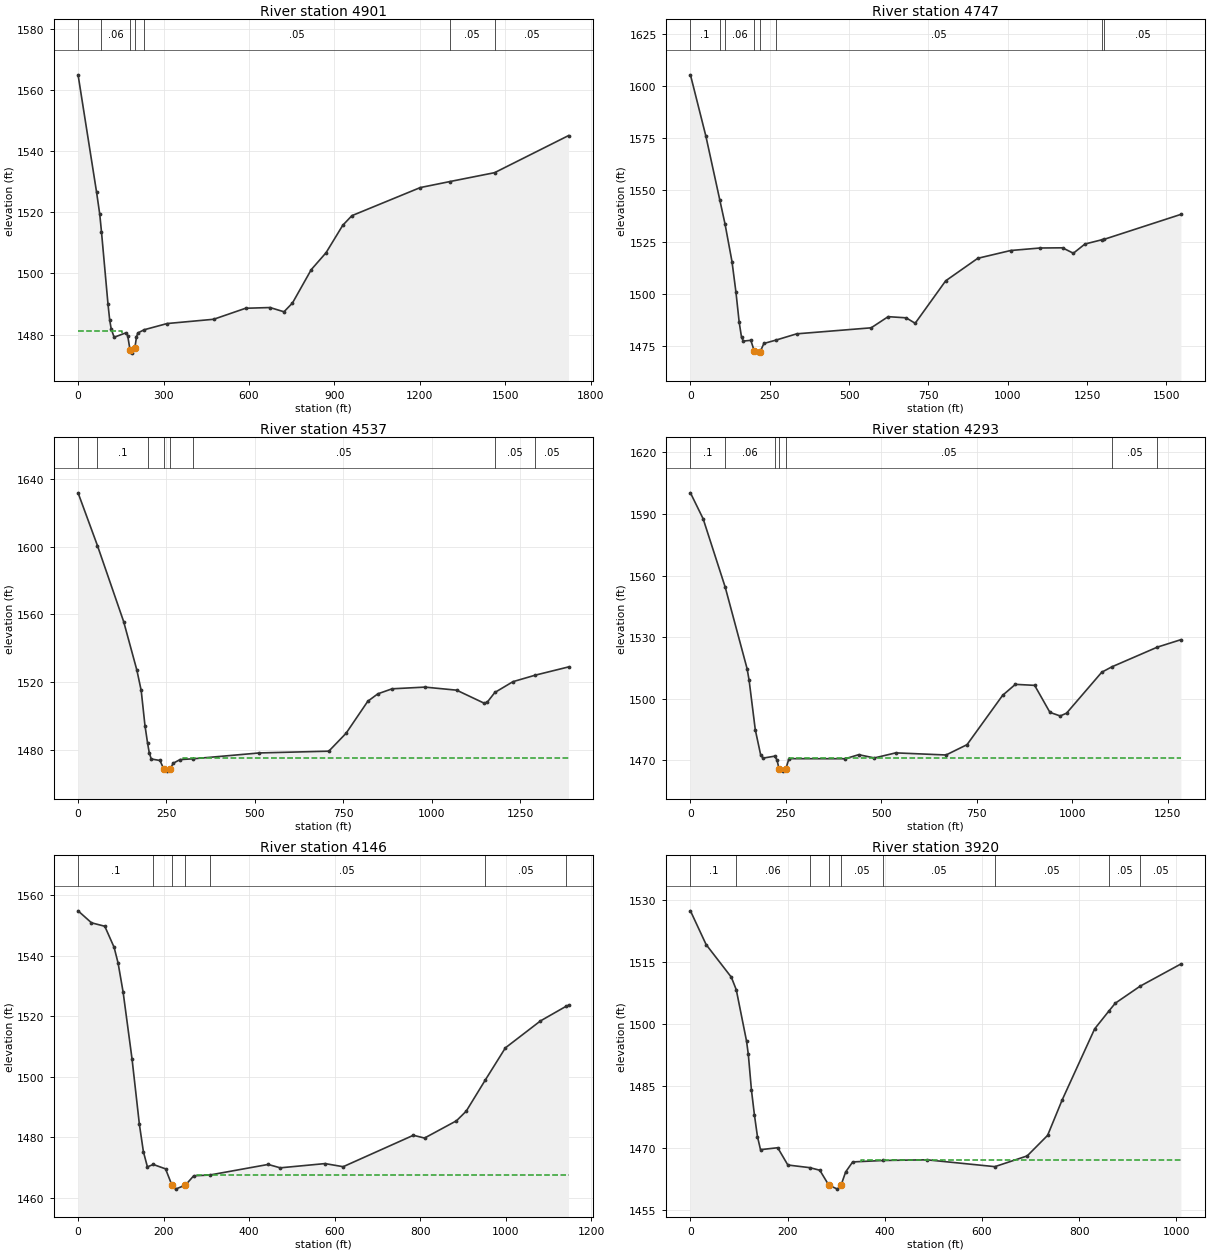
Type RM Length L Ch R = 1 ,4901    ,153.5,154,153.5
XS GIS Cut Line= 4
 2488149.1481418620803.3916437482488225.53703064620848.530532643
2488760.25925291621289.5027548522489465.12036401621911.030532658
#Sta/Elev= 30
       0 1564.96    65.1 1526.51    76.2 1519.31   82.251513.573     105 1490.02
     111  1484.8   116.2 1481.91   126.6 1479.14   168.1 1480.59   174.2 1479.63
   182.2 1475.11   188.8 1473.95   199.2 1475.54   204.9 1479.12   209.5 1480.52
  231.731481.586   312.9 1483.63   475.9 1485.02     588 1488.62   673.8 1488.86
   722.8 1487.47   752.6 1490.35   818.6 1501.27   870.5 1506.79   929.1 1515.76
   961.1  1518.9  1201.2 1528.09  1305.51530.065 1462.011532.9621721.574 1545.09
#Mann= 7 ,-1 , 0
       0      .1       0   82.25     .06       0   182.2    .045       0
   199.2     .06       0  231.73     .05       0  1305.5     .05       0
 1462.01     .05       0
#XS Ineff= 2 , 0
          155.56 1481.03
Permanent Ineff=
       F       F
Bank Sta=182.2,199.2
XS Rating Curve= 0 ,0
Exp/Cntr(USF)=0,0
Exp/Cntr=0.3,0.1

Type RM Length L Ch R = 1 ,4747    ,210.3,210.5,210.3
XS GIS Cut Line= 4
2488058.87036401620893.6694215392488142.20369732620970.058310419
 2488680.3981418621473.5305326582489145.67591956621990.891643748
#Sta/Elev= 30
       0 1605.43    48.7  1575.9   92.871544.956  108.881533.719     131 1515.51
   143.5 1500.73   153.6 1486.37   161.1 1478.98     167 1477.21   190.4 1477.57
   201.4 1472.32   213.1  1471.4   219.7    1472   231.4 1476.04  271.231477.751
   334.8 1480.69   569.6 1483.59   623.2 1488.96     680  1488.4   708.3 1485.77
   804.5 1506.23   905.7 1517.07  1009.1 1520.82  1101.9 1522.03  1172.7 1522.12
  1206.9 1519.51  1243.5 1523.95 1297.181526.013 1303.251526.1781545.832 1538.22
#Mann= 8 ,-1 , 0
       0      .1       0   92.87      .1       0  108.88     .06       0
   201.4    .045       0   219.7     .06       0  271.23     .05       0
 1297.18     .05       0 1303.25     .05       0
Bank Sta=201.4,219.7
XS Rating Curve= 0 ,0
Exp/Cntr(USF)=0,0
Exp/Cntr=0.3,0.1

Type RM Length L Ch R = 1 ,4537    ,244.1,244.1,244.1
XS GIS Cut Line= 4
2487881.78703064621056.8638659722488013.73147511621140.197199315
2488517.20369735621577.6971993152488885.25925291622004.780532643
#Sta/Elev= 30
       0  1631.6    54.71600.598   128.9 1555.83   166.3 1527.24   178.5  1515.3
   189.2 1494.63  196.511484.364   201.2 1478.76   206.9 1474.97   231.6 1474.09
   242.2 1469.14   251.6 1467.83   260.8 1469.03   268.7 1472.43   288.2 1474.61
  324.171475.072   512.4 1478.53     709 1479.57   757.8  1490.1   819.3 1508.96
   847.7 1513.32     888 1516.28     981 1517.27  1070.5 1515.47  1148.3 1507.81
  1157.3 1508.48 1178.431514.106  1229.8 1520.48 1293.351524.3351386.853 1529.15
#Mann= 8 ,-1 , 0
       0      .1       0    54.7      .1       0  196.51     .06       0
   242.2    .045       0   260.8     .06       0  324.17     .05       0
 1178.43     .05       0 1293.35     .05       0
#XS Ineff= 2 , 0
                          297.67         1475.28
Permanent Ineff=
       F       F
Bank Sta=242.2,260.8
XS Rating Curve= 0 ,0
Exp/Cntr(USF)=0,0
Exp/Cntr=0.3,0.1

Type RM Length L Ch R = 1 ,4293    ,146.7,146.7,146.7
XS GIS Cut Line= 4
2487753.31480843621240.8916437482487843.59258622621317.280532658
2488381.78703067621768.6694215392488704.70369735622102.002754867
#Sta/Elev= 30
       0 1600.26    33.3 1587.62   91.191554.279   148.5  1514.6   153.7 1509.02
   169.9  1484.9   184.1 1472.58   190.2 1471.09  220.691472.046   226.7 1470.22
     232 1466.01   243.7 1464.76   249.4  1465.6   258.1 1470.83   405.6 1470.79
   440.8 1472.77   481.8 1471.18   537.8 1473.65   669.6 1472.62   724.6 1477.65
   817.9 1501.69   851.2 1507.01   901.7 1506.52   941.7 1493.37   968.6 1491.62
   985.3 1492.98  1077.5 1512.92 1103.851515.526 1223.311525.1471284.785 1528.76
#Mann= 7 ,-1 , 0
       0      .1       0   91.19     .06       0  220.69     .05       0
     232    .045       0   249.4     .05       0 1103.85     .05       0
 1223.31     .05       0
#XS Ineff= 2 , 0
                          258.45         1470.92
Permanent Ineff=
       F       F
Bank Sta=232,249.4
XS Rating Curve= 0 ,0
Exp/Cntr(USF)=0,0
Exp/Cntr=0.3,0.1

Type RM Length L Ch R = 1 ,4146    ,226.7,226.7,226.7
XS GIS Cut Line= 4
2487666.50925291621414.5027548522487781.09258625621470.058310419
2488100.53703064621667.9749770762488534.56480843622143.669421539
#Sta/Elev= 30
       0 1554.79    31.4 1550.83    62.5 1549.69    84.3 1542.73    93.6 1537.53
   105.3    1528   126.2 1505.88   143.4 1484.23   152.8 1475.19   162.2 1470.16
  175.871470.957   204.6 1469.51   219.2 1464.23   227.9 1462.81   251.2 1464.15
   270.5 1467.22  307.451467.461   444.6 1470.97   472.8 1469.85   577.6 1471.25
     620 1470.22   784.2 1480.61   810.3 1479.69     885  1485.4   907.8 1488.58
  951.731498.718   999.4  1509.5  1081.5 1518.41  1140.81523.1951147.073  1523.6
#Mann= 7 ,-1 , 0
       0      .1       0  175.87     .06       0   219.2    .045       0
   251.2     .06       0  307.45     .05       0  951.73     .05       0
  1140.8     .05       0
#XS Ineff= 2 , 0
                          278.91         1467.58
Permanent Ineff=
       F       F
Bank Sta=219.2,251.2
XS Rating Curve= 0 ,0
Exp/Cntr(USF)=0,0
Exp/Cntr=0.3,0.1

Type RM Length L Ch R = 1 ,3920    ,159.2,159.2,159.2
XS GIS Cut Line= 4
2487565.81480846621542.9749770912487645.67591956  621608.9471993
2487933.87036401621848.5305326582488291.50925288622240.891643763
#Sta/Elev= 30
       0 1527.33    32.3 1519.17    84.2 1511.28   94.331508.248   115.4 1495.88
   119.1 1492.65   125.6 1483.95   131.7 1477.98   137.9 1472.76   144.2 1469.58
   179.6 1470.05   200.5 1465.87  245.521465.233   266.2 1464.61   284.7 1461.01
   302.6 1460.04   310.2 1461.08   319.4 1464.19   333.9 1466.62  396.741466.964
   486.3 1467.13  626.481465.475     693 1468.07     735 1473.04   764.7 1481.54
   831.8 1498.79  860.46 1503.01   874.2 1504.99   925.31509.1061009.259 1514.48
#Mann= 9 ,-1 , 0
       0      .1       0   94.33     .06       0  245.52     .05       0
   284.7    .045       0   310.2     .05       0  396.74     .05       0
  626.48     .05       0  860.46     .05       0   925.3     .05       0
#XS Ineff= 2 , 0
                          350.62          1467.1
Permanent Ineff=
       F       F
Bank Sta=284.7,310.2
XS Rating Curve= 0 ,0
Exp/Cntr(USF)=0,0
Exp/Cntr=0.3,0.1

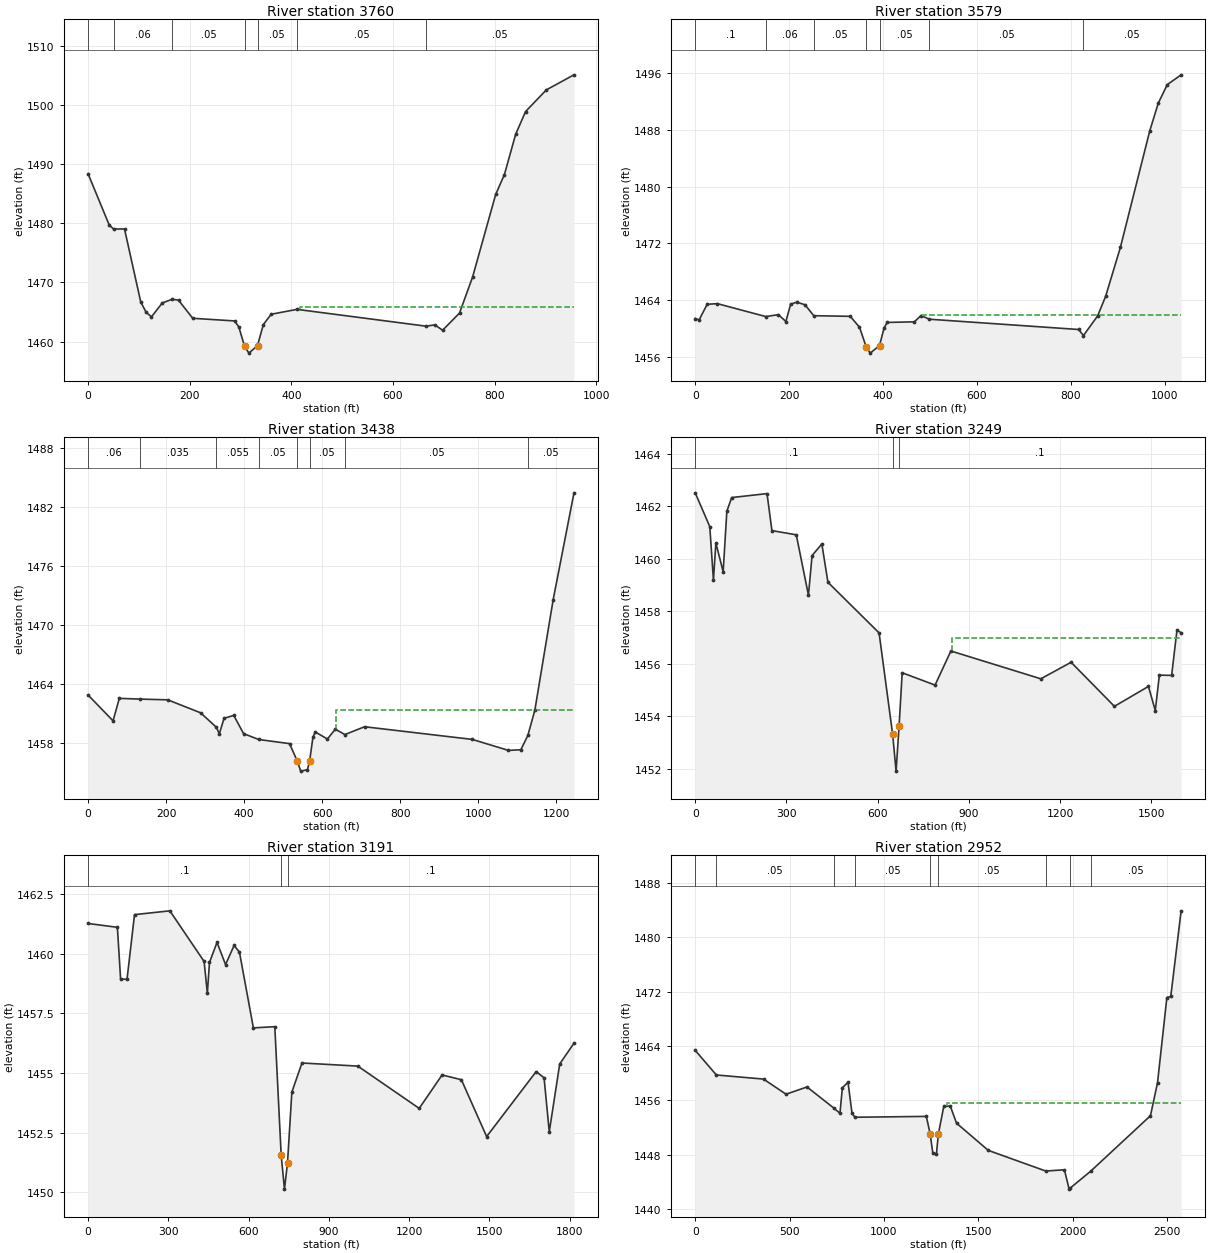
Type RM Length L Ch R = 1 ,3760    ,181.5,181.5,181.5
XS GIS Cut Line= 4
2487461.64814177  621608.94719932487583.17591953621747.836088195
2487847.06480843 621997.836088212488097.06480843622320.752754852
#Sta/Elev= 30
       0 1488.37    41.8 1479.66   50.371479.034    71.7 1479.04   103.6 1466.72
   114.2 1464.96   124.8 1464.19   146.1 1466.54  165.83 1467.16     178    1467
     206 1463.94   288.6 1463.49   296.8 1462.45   308.1 1459.18   316.6 1458.05
   333.5 1459.33   344.9 1462.87   360.3 1464.62  411.171465.448  665.231462.607
   682.6 1462.83   697.8 1461.92   731.1 1464.82   756.8  1470.9   802.3 1484.87
   819.5 1488.24   841.6 1495.04   861.2  1498.9   902.1 1502.56956.4393  1505.1
#Mann= 7 ,-1 , 0
       0      .1       0   50.37     .06       0  165.83     .05       0
   308.1    .045       0   333.5     .05       0  411.17     .05       0
  665.23     .05       0
#XS Ineff= 2 , 0
                          417.01         1465.83
Permanent Ineff=
       F       F
Bank Sta=308.1,333.5
XS Rating Curve= 0 ,0
Exp/Cntr(USF)=0,0
Exp/Cntr=0.3,0.1

Type RM Length L Ch R = 1 ,3579    ,140.6,140.6,140.6
XS GIS Cut Line= 4
2487357.48147511621619.3638659722487447.75925291621834.641643748
2487680.39814177622136.7249770912488010.25925291622397.141643763
#Sta/Elev= 30
       0 1461.46     8.2 1461.26    25.5 1463.46    47.2 1463.55  150.181461.738
   177.3    1462   193.1 1461.04   203.3 1463.48   216.4 1463.76   233.8 1463.39
  252.521461.857   330.1 1461.77   349.9 1460.25   364.1 1457.49   372.7  1456.6
   392.6 1457.67   402.2 1460.11   408.8 1460.91   466.8    1461     481 1461.88
  498.581461.364   816.5 1459.92  826.991459.074   857.2 1461.83   874.2 1464.58
   905.6 1471.44   968.2 1487.82   986.2 1491.69  1005.5 1494.31 1034.99 1495.69
#Mann= 7 ,-1 , 0
       0      .1       0  150.18     .06       0  252.52     .05       0
   364.1    .045       0   392.6     .05       0  498.58     .05       0
  826.99     .05       0
#XS Ineff= 2 , 0
                          483.95          1461.9
Permanent Ineff=
       F       F
Bank Sta=364.1,392.6
XS Rating Curve= 0 ,0
Exp/Cntr(USF)=0,0
Exp/Cntr=0.3,0.1

Type RM Length L Ch R = 1 ,3438    ,179.8,189.3,199.1
XS GIS Cut Line= 4
2487301.92591956621542.9749770912487319.28703064621890.197199315
2487610.95369732 622279.086088212487975.53703064622470.058310434
#Sta/Elev= 30
       0 1462.89      64 1460.26      80 1462.55  132.961462.476   204.2  1462.4
   288.3 1461.08  329.091459.592   336.3 1458.94   348.5 1460.52   373.4 1460.81
   398.5 1458.96  437.241458.361   516.3 1457.94   536.3 1456.15   544.9 1455.14
   562.1 1455.28   567.8 1456.18   576.3 1458.59   582.1 1459.13   613.4 1458.41
   633.5 1459.41  658.261458.863   708.5 1459.66   984.6 1458.37  1077.4 1457.25
  1109.2 1457.32 1127.131458.777  1145.1 1461.36    1192  1472.61245.339 1483.48
#Mann= 8 ,-1 , 0
       0     .06       0  132.96    .035       0  329.09    .055       0
  437.24     .05       0   536.3    .045       0   567.8     .05       0
  658.26     .05       0 1127.13     .05       0
#XS Ineff= 2 , 0
       0  368.72 1460.17  635.73       0 1461.33
Permanent Ineff=
       F       F
Bank Sta=536.3,567.8
XS Rating Curve= 0 ,0
Exp/Cntr(USF)=0,0
Exp/Cntr=0.5,0.3

Type RM Length L Ch R = 1 ,3249    ,57,58.3,59.5
XS GIS Cut Line= 4
2487280.87687655621519.0670326842487309.59932147 622078.30993069
2487302.84109913622309.7790455752488022.59177753622673.033495942
#Sta/Elev= 30
       0 1462.52    47.9 1461.23    59.9 1459.19    67.9 1460.61    91.9 1459.51
     104 1461.82     120 1462.34   236.1 1462.49   252.2 1461.08   332.3 1460.92
   372.3 1458.62   384.3 1460.13   416.4 1460.57   436.4 1459.11   604.6 1457.18
   649.21453.311   660.5 1451.91   670.31453.612   680.6 1455.66   788.7 1455.19
   840.7 1456.49  1136.4 1455.43    1236 1456.06  1378.4 1454.38  1490.4 1455.14
  1512.8 1454.22  1526.3 1455.57  1566.6 1455.56  1584.1 1457.28  1597.8 1457.19
#Mann= 3 , 0 , 0
       0      .1       0   649.2    .045       0   670.3      .1       0
#XS Ineff= 2 , 0
                          843.67         1456.99
Permanent Ineff=
       F       F
Bank Sta=649.2,670.3
XS Rating Curve= 0 ,0
Exp/Cntr(USF)=0,0
Exp/Cntr=0.5,0.3

Type RM Length L Ch R = 1 ,3191    ,242,238.5,226.4
XS GIS Cut Line= 4
2487243.70665372 621473.449031942487262.29176514622079.999486273
2487248.77532047622370.6030465672488064.83066711622791.302386759
#Sta/Elev= 30
       0 1461.26   109.5  1461.1   121.5 1458.94   145.5 1458.92   173.5 1461.63
   305.6 1461.79   433.6 1459.67   445.7 1458.34   453.7 1459.63   481.9 1460.47
   513.7 1459.54   545.7 1460.34   565.7 1460.06   617.7 1456.89   697.8 1456.94
   721.61451.563   733.9 1450.14   745.41451.251   761.5  1454.2   799.3 1455.42
    1008 1455.29  1237.5 1453.52    1323 1454.92    1395 1454.72  1489.5 1452.34
  1674.5 1455.06  1704.1  1454.8  1723.5 1452.54  1762.6 1455.38  1815.9 1456.25
#Mann= 3 , 0 , 0
       0      .1       0   721.6    .045       0   745.4      .1       0
#XS Ineff= 2 , 0
                          802.97         1455.33
Permanent Ineff=
       F       F
Bank Sta=721.6,745.4
XS Rating Curve= 0 ,0
Exp/Cntr(USF)=0,0
Exp/Cntr=0.5,0.3

Type RM Length L Ch R = 1 ,2952    ,621,621,621
XS GIS Cut Line= 4
 2487232.3742862621235.4038660422486914.39866977622095.095307346
2487462.80623205622904.9529865312488119.61994036623083.504285879
#Sta/Elev= 30
       0 1463.36  112.011459.735     362 1459.13   481.4  1456.9   592.4 1457.97
  734.811454.856   767.1 1454.09   779.9 1457.84   809.8 1458.67   831.1 1454.07
  846.461453.505  1224.9 1453.63  1245.1 1451.07  1259.5 1448.19  1278.7 1448.16
  1288.6 1451.02  1317.3 1455.09  1351.6 1455.17    1385 1452.63  1553.3 1448.62
 1858.011445.576  1956.8 1445.76  1981.7 1442.91  1986.8 1443.05 2095.871445.549
  2412.8 1453.73  2450.3  1458.6  2499.8 1471.14  2520.5 1471.312575.332 1483.93
#Mann= 9 ,-1 , 0
       0     .06       0  112.01     .05       0  734.81     .06       0
  846.46     .05       0  1245.1    .045       0  1288.6     .05       0
 1858.01      .1       0  1986.8     .05       0 2095.87     .05       0
#XS Ineff= 2 , 0
                         1333.33         1455.59
Permanent Ineff=
       F       F
Bank Sta=1245.1,1288.6
XS Rating Curve= 0 ,0
Exp/Cntr(USF)=0,0
Exp/Cntr=0.3,0.1

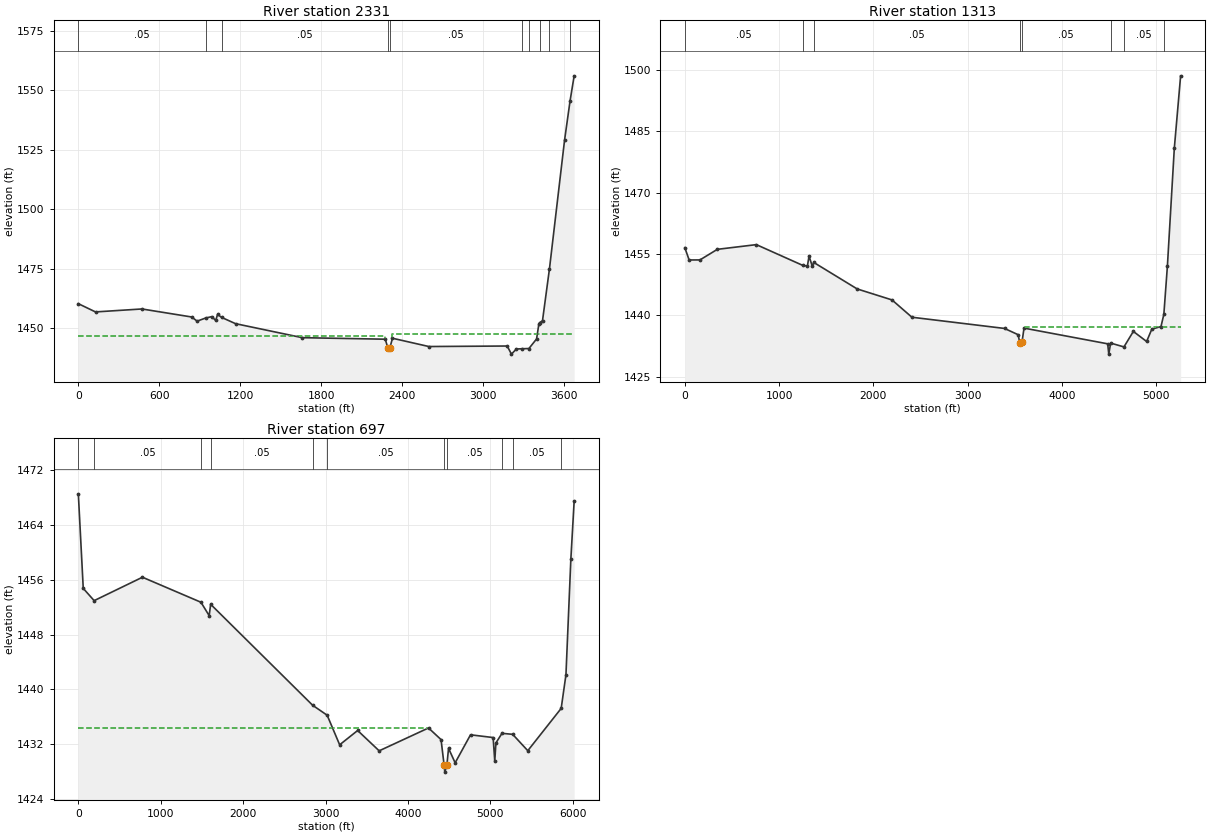
Type RM Length L Ch R = 1 ,2331    ,1017.5,1017.5,1017.5
XS GIS Cut Line= 4
2487226.86344363  621004.6570149 2486468.0204214622554.227219955
2487067.44264064623128.1421107162487921.93814466623848.724140227
#Sta/Elev= 30
       0 1460.34   127.2 1456.88   471.2 1458.12   839.8 1454.75   879.9    1453
  942.981454.318   988.4  1454.9    1018 1453.29  1031.3 1455.82 1061.931454.563
  1164.8 1451.94  1659.3 1446.06  2273.8 1445.42  2293.2 1441.67 2306.81  1441.6
  2327.3 1445.82  2596.8 1442.34    3177 1442.56  3208.4 1439.15    3245  1441.3
 3287.67 1441.41  3337.9  1441.5  3394.6 1445.53  3411.2 1451.65 3416.971452.324
  3438.6 1453.23 3490.361475.116  3601.9 1529.01 3642.811545.5723673.038 1556.06
#Mann= 10 ,-1 , 0
       0     .05       0  942.98     .06       0 1061.93     .05       0
  2293.2    .045       0 2306.81     .05       0 3287.67     .05       0
  3337.9      .1       0 3416.97     .05       0 3490.36      .1       0
 3642.81      .1       0
#XS Ineff= 2 , 0
       0  2273.8 1446.96  2327.3       0 1447.56
Permanent Ineff=
       F       F
Bank Sta=2293.2,2306.81
XS Rating Curve= 0 ,0
Exp/Cntr(USF)=0,0
Exp/Cntr=0.3,0.1

Type RM Length L Ch R = 1 ,1313    ,615.8,615.8,615.8
XS GIS Cut Line= 4
2487241.74271857620729.0361599552486171.85199629623060.122568107
2487050.43775498624477.1963724552487893.59666857 625065.28200126
#Sta/Elev= 30
       0 1456.54    46.1 1453.52   160.5 1453.53   345.3 1456.12     759 1457.27
 1250.851452.202  1300.8 1452.04    1318 1454.46  1353.2 1451.94 1367.791452.923
  1828.5 1446.44  2198.2 1443.75  2409.5 1439.52  3391.8 1436.78  3536.4 1435.25
  3553.1 1433.33  3577.1 1433.39  3598.8 1436.86  4486.5 1433.02    4498  1430.5
 4517.81  1433.2 4658.931432.264  4758.6 1436.05  4899.4 1433.59  4954.8 1436.61
  5051.9 1437.25 5082.291440.224  5120.2 1452.12  5193.2  1480.85260.209 1498.54
#Mann= 8 ,-1 , 0
       0     .05       0 1250.85     .06       0 1367.79     .05       0
  3553.1    .045       0  3577.1     .05       0 4517.81     .05       0
 4658.93     .05       0 5082.29     .05       0
#XS Ineff= 2 , 0
                         3610.42         1437.23
Permanent Ineff=
       F       F
Bank Sta=3553.1,3577.1
XS Rating Curve= 0 ,0
Exp/Cntr(USF)=0,0
Exp/Cntr=0.3,0.1

Type RM Length L Ch R = 1 ,697     ,,,
XS GIS Cut Line= 5
2487286.67503817620531.365055477 2485837.0989258623596.075626176
2486388.05722093624393.817324334 2486738.1453043624657.818174084
2487845.80104347625168.602426861
#Sta/Elev= 30
       0 1468.57    59.7 1454.76  191.961452.972   778.3 1456.39 1488.211452.737
    1588 1450.78 1606.05 1452.44 2844.131437.692 3020.151436.239  3171.8 1431.92
  3390.2 1434.01  3651.3 1431.04  4250.3 1434.38  4402.4 1432.68  4439.5 1428.97
  4448.1 1427.93  4473.8 1429.02  4493.4  1431.4  4573.5 1429.29  4760.1 1433.38
  5034.6 1432.98  5054.4 1429.54  5068.2 1432.19 5142.111433.597 5271.65 1433.45
  5455.2 1431.06  5860.6 1437.24  5918.4 1442.15  5978.2 1459.116017.975  1467.5
#Mann= 11 ,-1 , 0
       0      .1       0  191.96     .05       0 1488.21     .06       0
 1606.05     .05       0 2844.13     .05       0 3020.15     .05       0
  4439.5    .045       0  4473.8     .05       0 5142.11     .05       0
 5271.65     .05       0  5860.6     .05       0
#XS Ineff= 2 , 0
         4234.57 1434.39 4772.29         1432.92
Permanent Ineff=
       F       F
Bank Sta=4439.5,4473.8
XS Rating Curve= 0 ,0
Exp/Cntr(USF)=0,0
Exp/Cntr=0.3,0.1
LCMann Table=0

Chan Stop Cuts=-1
Use User Specified Reach Order=0
Composite Channel Slope=5